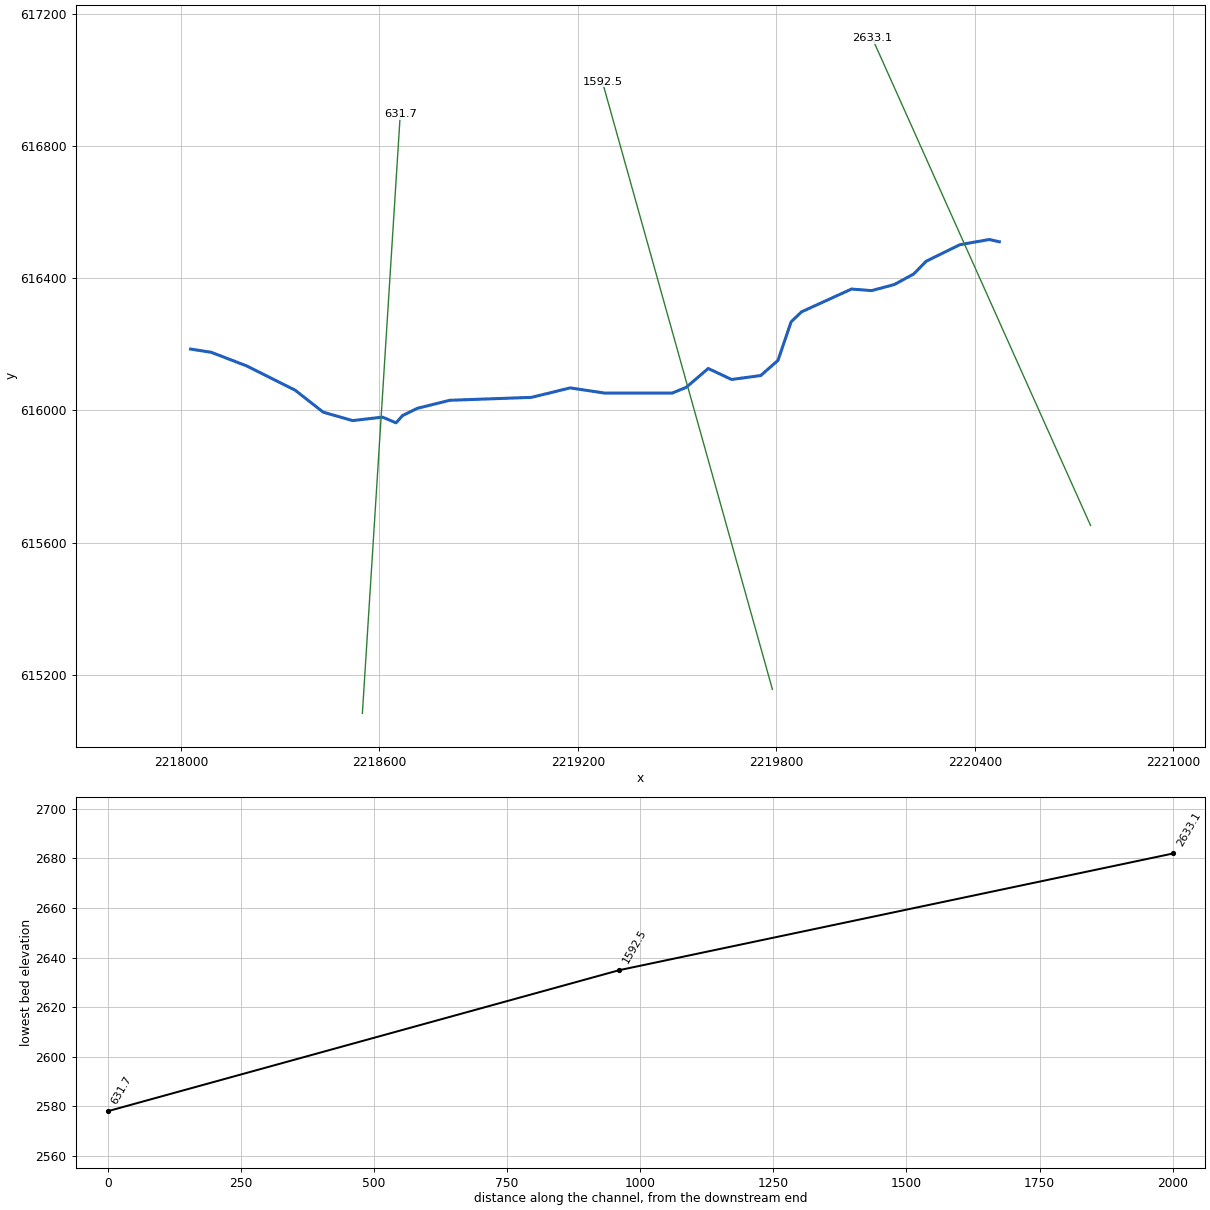
--- LICKRN.prj (project) ---

Proj Title=LICKRN
Current Plan=p01
Geom File=g01
Flow File=f01
Plan File=p01
DSS Export Rating Curves=0
DSS Export Rating Curve Sorted=0
DSS Export Volume Flow Curves=0
DXF OffsetX=0
DXF OffsetY=0
DXF ScaleX=0
DXF ScaleY=0

--- LICKRN.p01 (plan) ---

Plan Title=Floodplain
Program Version=4.00
Geom File=g01
Flow File=f01
K Sum by GR=0
Std Step Tol=0.01
Critical Tol=0.01
Num of Std Step Trials=20
Max Error Tol=0.3
Flow Tol Ratio=0.001
Split Flow NTrial=30
Split Flow Tol=0.02
Split Flow Ratio=0.02
Log Output Level=0
Friction Slope Method=1
Unsteady Friction Slope Method=2
Unsteady Bridges Friction Slope Method=1
Global Log Level=0
CheckData=False
Run HTab=0
Run UNet=0
Run PostProcess=0
UNET Theta=0
UNET Theta Warmup=0
UNET ZTol=0
UNET ZSATol=0
UNET MxIter=0
UNET MaxInSteps=0
UNET DtIC=0
UNET DtMin=0
UNET MaxCRTS=0
UNET WFStab=0
UNET SFStab=0
UNET WFX=0
UNET SFX=0
UNET DSS MLevel=0
UNET DZMax Abort=0
UNET Convert EG Bridges=0
UNET Use Existing IB Tables=0
UNET Froude Limit=0
UNET Froude Power=0
Write IC File=0
Echo Input=False
Echo Output=False
Write Detailed=0

--- LICKRN.f01 (steady flow) ---

Flow Title=Flow
Program Version=4.00
Number of Profiles=1
Profile Names=P100yr
River Rch & RM=LICKRN,Main      ,2633.1
303.7828
River Rch & RM=LICKRN,Main      ,1592.5
326.4331
River Rch & RM=LICKRN,Main      ,1592.5
311.7257
River Rch & RM=LICKRN,Main      ,631.7
371.4341
River Rch & RM=LICKRN,Main      ,631.7
375.0799
River Rch & RM=LICKRN,Main      ,631.7
362.3018
River Rch & RM=LICKRN,Main      ,631.7
368.1356
Boundary for River Rch & Prof#=LICKRN,Main      ,1
Up Type=0
Dn Type=3
Dn Slope=0.052225

--- LICKRN.g01 (geometry) ---

Geom Title=Geometry
Program Version=4.00

River Reach=LICKRN     ,Main
Reach XY= 30
     2220474.046      616511.142     2220443.670      616518.059
     2220354.521      616502.219     2220252.763      616452.130
     2220214.671      616413.226     2220156.338      616381.455
     2220087.588      616363.225     2220027.171      616367.913
     2219876.024      616298.919     2219844.510      616268.635
     2219804.776      616151.767     2219752.692      616105.934
     2219664.671      616093.955     2219593.838      616127.288
     2219527.171      616069.996     2219484.984      616052.809
     2219280.817      616052.809     2219176.650      616068.434
     2219059.463      616039.788     2218812.588      616030.934
     2218714.150      616006.455     2218669.661      615984.698
     2218650.206      615962.688     2218608.942      615979.892
     2218518.577      615969.373     2218429.775      615994.996
     2218344.879      616061.663     2218198.525      616135.100
     2218091.060      616176.420     2218028.838      616186.120

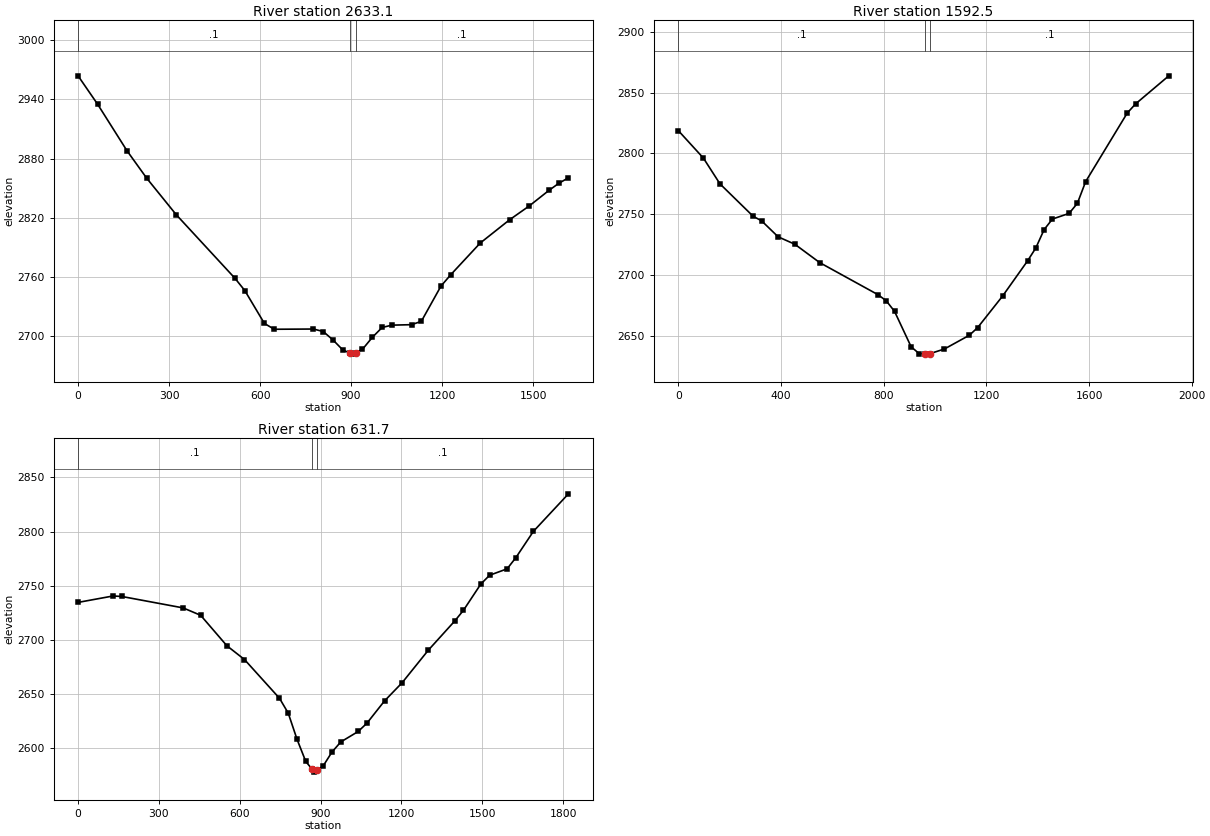
Type RM Length L Ch R = 1 ,2633.1,1042.1,1040.6,1033.7
XS GIS Cut Line= 2
     2220749.706      615651.832     2220089.984      617127.526
#Sta/Elev= 30
       0 2963.87    64.7 2934.99   161.6 2887.84   226.3 2860.18   323.3 2823.32
   517.3 2758.76   549.6 2746.40   614.2 2713.08   646.6 2707.19   775.9 2707.42
   808.2 2704.90   840.6 2696.27   872.9 2686.15   895.2 2683.28   905.2 2682.00
   915.2 2683.52   937.5 2686.91   969.9 2698.97  1002.2 2709.00  1034.5 2711.35
  1099.2 2711.83  1131.5 2715.21  1196.2 2750.91  1228.5 2762.44  1325.5 2794.48
  1422.5 2818.10  1487.1 2832.06  1551.8 2847.76  1584.1 2854.91  1616.4 2860.62
#Mann= 3 , 0 , 0
       0     0.1       0   895.2   0.045       0   915.2     0.1       0
Bank Sta=895.2,915.2
Exp/Cntr=0.3,0.1

Type RM Length L Ch R = 1 ,1592.5,968.3,960.8,948.7
XS GIS Cut Line= 2
     2219787.901      615155.304     2219274.012      616995.582
#Sta/Elev= 30
       0 2818.61    97.2 2796.15   161.9 2774.92   291.5 2748.19   323.8 2744.58
   388.6 2731.36   453.4 2725.30   550.5 2710.17   777.2 2683.84   809.6 2678.82
   842.0 2670.10   906.8 2640.92   939.2 2635.14   961.5 2634.99   971.5 2634.92
   981.5 2635.42  1036.3 2639.13  1133.5 2650.43  1165.8 2656.72  1263.0 2682.65
  1360.2 2711.54  1392.5 2722.20  1424.9 2737.33  1457.3 2746.00  1522.1 2750.62
  1554.4 2758.91  1586.8 2776.82  1748.8 2833.17  1781.1 2840.65  1910.7 2863.75
#Mann= 3 , 0 , 0
       0     0.1       0   961.5   0.045       0   981.5     0.1       0
Bank Sta=961.5,981.5
Exp/Cntr=0.3,0.1

Type RM Length L Ch R = 1 ,631.7,631.5,631.7,630.4
XS GIS Cut Line= 2
     2218548.317      615082.387     2218662.901      616898.359
#Sta/Elev= 30
       0 2734.62   130.0 2740.55   162.5 2740.08   389.9 2729.54   454.9 2722.72
   552.4 2694.57   617.4 2681.94   747.3 2646.20   779.8 2632.50   812.3 2608.45
   844.8 2587.91   867.3 2581.07   877.3 2578.03   887.3 2579.83   909.8 2583.87
   942.3 2596.60   974.8 2605.87  1039.8 2615.59  1072.2 2623.30  1137.2 2643.75
  1202.2 2660.43  1299.7 2690.55  1397.2 2717.33  1429.7 2727.21  1494.7 2751.64
  1527.2 2759.68  1592.1 2765.61  1624.6 2775.96  1689.6 2800.17  1819.6 2834.79
#Mann= 3 , 0 , 0
       0     0.1       0   867.3   0.045       0   887.3     0.1       0
Bank Sta=867.3,887.3
Exp/Cntr=0.3,0.1